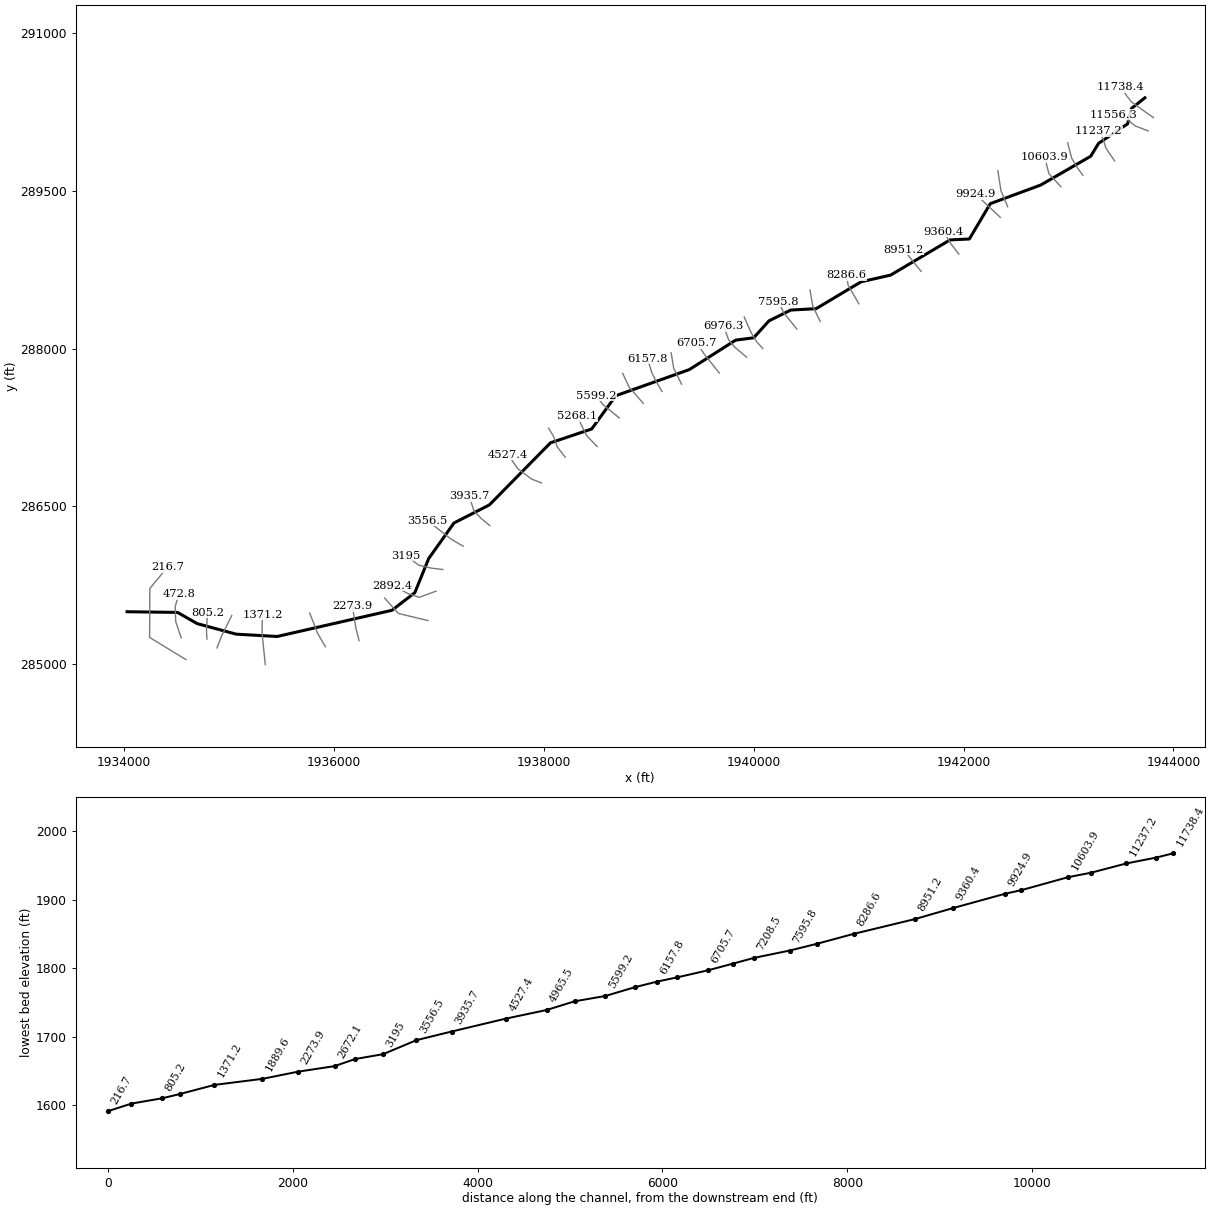
--- LIWOLFCK.prj (project) ---

Proj Title=LIWOLFCK
Current Plan=p01
Default Exp/Contr=0,0
English Units
Geom File=g01
Flow File=f01
Plan File=p01
BEGIN DESCRIPTION:
END DESCRIPTION:
DSS Export Rating Curves= 0
DSS Export Rating Curve Sorted= 0
DSS Export Volume Flow Curves= 0
DXF OffsetX= 0
DXF OffsetY= 0
DXF ScaleX= 0
DXF ScaleY= 0

--- LIWOLFCK.p01 (plan) ---

Plan Title=Floodplain
Program Version=4.00
Geom File=g01
Flow File=f01
K Sum by GR=0
Std Step Tol=0.01
Critical Tol=0.01
Num of Std Step Trials=20
Max Error Tol=0.3
Flow Tol Ratio=0.001
Split Flow NTrial=30
Split Flow Tol=0.02
Split Flow Ratio=0.02
Log Output Level=0
Friction Slope Method=1
Unsteady Friction Slope Method=2
Unsteady Bridges Friction Slope Method=1
Global Log Level=0
CheckData=False
Run HTab=0
Run UNet=0
Run PostProcess=0
UNET Theta=0
UNET Theta Warmup=0
UNET ZTol=0
UNET ZSATol=0
UNET MxIter=0
UNET MaxInSteps=0
UNET DtIC=0
UNET DtMin=0
UNET MaxCRTS=0
UNET WFStab=0
UNET SFStab=0
UNET WFX=0
UNET SFX=0
UNET DSS MLevel=0
UNET DZMax Abort=0
UNET Convert EG Bridges=0
UNET Use Existing IB Tables=0
UNET Froude Limit=0
UNET Froude Power=0
Write IC File=0
Echo Input=False
Echo Output=False
Write Detailed=0

--- LIWOLFCK.f01 (steady flow) ---

Flow Title=NFF Regression Equation
Program Version=4.10
Number of Profiles= 1
Profile Names=P100yr
River Rch & RM=LIWOLFCK,Main            ,11738.4
629.0421
River Rch & RM=LIWOLFCK,Main            ,10098.1
651.8425
River Rch & RM=LIWOLFCK,Main            ,8286.6
710.8193
River Rch & RM=LIWOLFCK,Main            ,5599.2
771.9536
River Rch & RM=LIWOLFCK,Main            ,2892.4
  836.36
River Rch & RM=LIWOLFCK,Main            ,2672.1
1265.431
River Rch & RM=LIWOLFCK,Main            ,216.7
1302.039
Boundary for River Rch & Prof#=LIWOLFCK,Main            , 1
Up Type= 0
Dn Type= 1
Dn Known WS=1596.07
DSS Import GetInterval= 0
DSS Import GetPeak= 0
DSS Import FillOption= 0

--- LIWOLFCK.g01 (geometry) ---

Geom Title=USGS 10m DEM
Program Version=4.10

River Reach=LIWOLFCK        ,Main
Reach XY= 30
     1943727.196      290387.217     1943599.158       290285.22
     1943563.351      290139.821     1943286.224      289954.057
     1943211.698       289831.23     1942734.358      289556.618
     1942254.757      289379.751     1942055.104       289043.38
     1941871.727      289034.699     1941304.453      288699.413
     1941023.203      288635.611     1940594.818      288379.751
     1940353.932       288366.73     1940145.599      288263.866
     1939999.766      288102.408     1939827.891      288080.272
     1939386.484      287799.673     1938685.964      287550.975
     1938456.797      287234.569     1938063.568      287102.408
     1937481.536      286511.262     1937144.297      286339.387
     1936903.411      286000.845      1936771.18      285675.892
     1936553.289      285508.123     1935459.401      285258.658
     1935068.776      285280.793     1934697.682      285381.053
     1934510.182      285487.824     1934029.714      285494.335

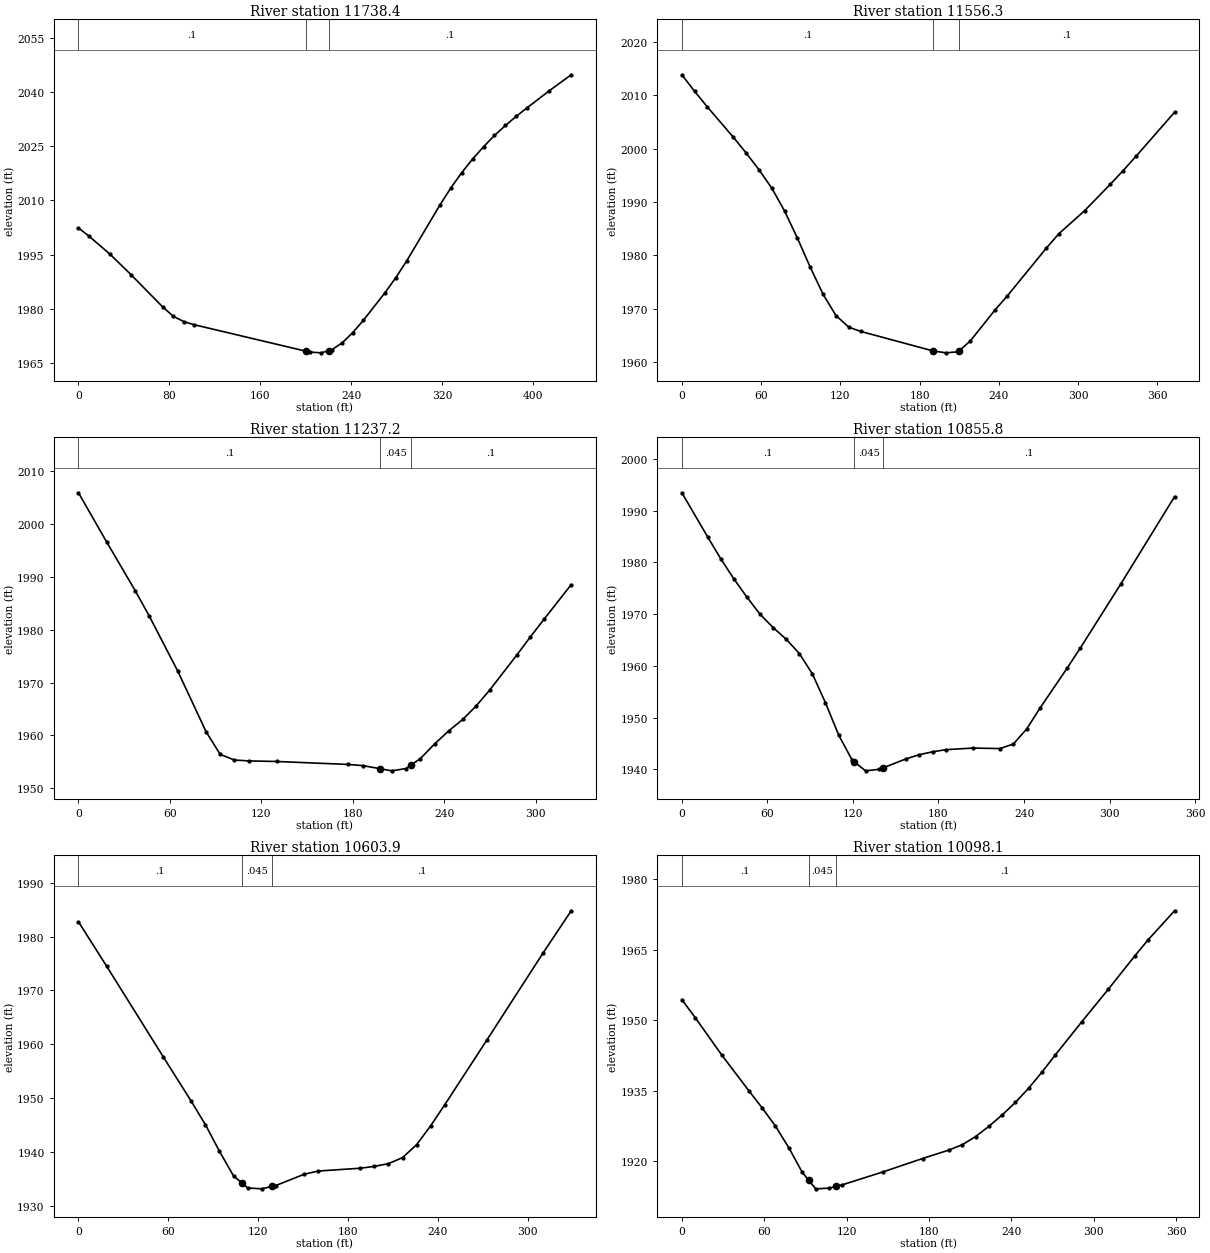
Type RM Length L Ch R = 1 ,11738.4 ,182.4,182,181.8
XS GIS Cut Line= 4
     1943809.383      290199.051     1943687.855      290284.121
     1943597.577      290350.093     1943493.411      290488.982
#Sta/Elev= 30
       0 2002.39     9.3 2000.14    27.8 1995.14    46.4 1989.45    74.2 1980.57
    83.4 1978.01    92.7 1976.53     102 1975.66   200.4 1968.34   204.2 1968.11
   213.6  1967.9   220.4  1968.5   222.9 1968.72   232.2 1970.68   241.5  1973.5
   250.8 1976.88   269.8 1984.49   279.4 1988.69   289.1 1993.37     318 2008.64
   327.7 2013.41   337.3 2017.66     347 2021.46   356.6 2024.83   366.2 2027.97
   375.9 2030.73   385.5 2033.29   395.2 2035.67   414.5 2040.33   433.8 2044.74
#Mann= 3 , 0 , 0
       0      .1       0   200.4    .045       0   220.4      .1       0
Bank Sta=200.4,220.4
XS Rating Curve= 0 ,0
Exp/Cntr=0.3,0.1

Type RM Length L Ch R = 1 ,11556.3 ,334.4,319.2,302.8
XS GIS Cut Line= 4
     1943759.036      290072.315      1943640.98      290117.454
     1943552.439      290183.426     1943423.966      290228.565
#Sta/Elev= 28
       0 2013.83     9.7 2010.72    19.4 2007.78    38.9 2002.16    48.6  1999.2
    58.3 1996.08    68.1 1992.59    77.8  1988.3    87.5 1983.22    97.2 1977.78
     107 1972.67   116.7 1968.72   126.4 1966.54   135.6 1965.74   190.1  1962.1
     200 1961.74   209.2 1961.94   210.1 1962.14   218.4 1963.98   236.8 1969.69
   246.5 1972.44   275.7 1981.29   285.4 1984.05   304.9 1988.37   324.4 1993.33
   334.1 1995.89   343.8 1998.56     373 2006.81
#Mann= 3 , 0 , 0
       0      .1       0   190.1    .045       0   210.1      .1       0
Bank Sta=190.1,210.1
XS Rating Curve= 0 ,0
Exp/Cntr=0.3,0.1

Type RM Length L Ch R = 1 ,11237.2 ,375.8,381.4,387
XS GIS Cut Line= 4
     1943439.591      289785.857     1943356.258      289909.121
      1943328.48      289999.398      1943288.55      290068.843
#Sta/Elev= 26
       0 2005.93    18.6 1996.56    37.2 1987.41    46.5 1982.56    65.1  1972.2
    83.7 1960.72      93  1956.4   102.3 1955.33   111.6 1955.16   130.2 1955.05
   177.1 1954.49   186.6 1954.27   198.1 1953.68   205.5 1953.28   214.9 1953.71
   218.1 1954.35   224.4  1955.6   233.8 1958.39   243.2  1960.9   252.2 1963.01
     261 1965.56     270 1968.61   287.8 1975.25   296.6 1978.64   305.6    1982
   323.4 1988.54
#Mann= 3 , 0 , 0
       0      .1       0   198.1    .045       0   218.1      .1       0
Bank Sta=198.1,218.1
XS Rating Curve= 0 ,0
Exp/Cntr=0.3,0.1

Type RM Length L Ch R = 1 ,10855.8 ,246.2,251.9,257.3
XS GIS Cut Line= 4
     1943135.772       289650.44     1943076.744      289732.037
     1943029.869      289813.634     1942991.675      289959.468
#Sta/Elev= 30
       0 1993.43    18.3 1984.82    27.5 1980.59    36.6 1976.76    45.8 1973.22
    54.9 1969.96    64.1 1967.38    73.2 1965.15    82.4 1962.39    91.6 1958.44
   100.7  1952.9   110.1 1946.59   119.5 1941.79     121 1941.46   128.9 1939.74
   138.4 1940.04     141  1940.3   157.2 1942.05   166.6 1942.86     176 1943.43
   185.4 1943.83   204.2 1944.14   223.1 1944.04   232.5 1944.91   241.9 1947.84
   251.3 1951.89   270.2 1959.55   279.6  1963.5   307.9 1975.83   345.6 1992.69
#Mann= 3 , 0 , 0
       0      .1       0     121    .045       0     141      .1       0
Bank Sta=121,141
XS Rating Curve= 0 ,0
Exp/Cntr=0.3,0.1

Type RM Length L Ch R = 1 ,10603.9 ,514.5,505.8,497.2
XS GIS Cut Line= 3
     1942927.439      289541.065     1942812.855      289666.065
     1942772.925      289820.579
#Sta/Elev= 24
       0 1982.77    18.8 1974.53    56.5 1957.72    75.4 1949.37    84.8 1945.03
    94.2 1940.09   103.6  1935.5   109.1  1934.2     113 1933.27   122.5  1933.1
   129.1 1933.54   131.9 1933.72   150.7 1935.81   160.2 1936.41   188.4 1936.94
   197.7 1937.28   207.1 1937.79   216.5 1938.91   225.9 1941.31   235.3 1944.83
   244.7 1948.74   272.8 1960.76   310.4 1976.98   329.2 1984.83
#Mann= 3 , 0 , 0
       0      .1       0   109.1    .045       0   129.1      .1       0
Bank Sta=109.1,129.1
XS Rating Curve= 0 ,0
Exp/Cntr=0.3,0.1

Type RM Length L Ch R = 1 ,10098.1 ,162.6,173.2,183.7
XS GIS Cut Line= 3
     1942420.494      289350.093     1942356.258      289502.871
     1942326.744      289693.843
#Sta/Elev= 29
       0 1954.38     9.8 1950.52    29.2 1942.54    48.7 1935.04    58.5 1931.35
    68.2 1927.47      78 1922.84    87.7 1917.66    92.3    1916    97.5 1914.13
   107.2 1914.28   112.3 1914.65     117 1914.99   146.2  1917.7   175.4 1920.58
   194.7 1922.39   204.4 1923.53     214 1925.24   223.7 1927.43   233.4 1929.85
     243 1932.51   252.7 1935.54   262.4 1938.96     272 1942.57   291.3 1949.63
   310.7 1956.57     330 1963.66   339.6 1967.05     359 1973.27
#Mann= 3 , 0 , 0
       0      .1       0    92.3    .045       0   112.3      .1       0
Bank Sta=92.3,112.3
XS Rating Curve= 0 ,0
Exp/Cntr=0.3,0.1

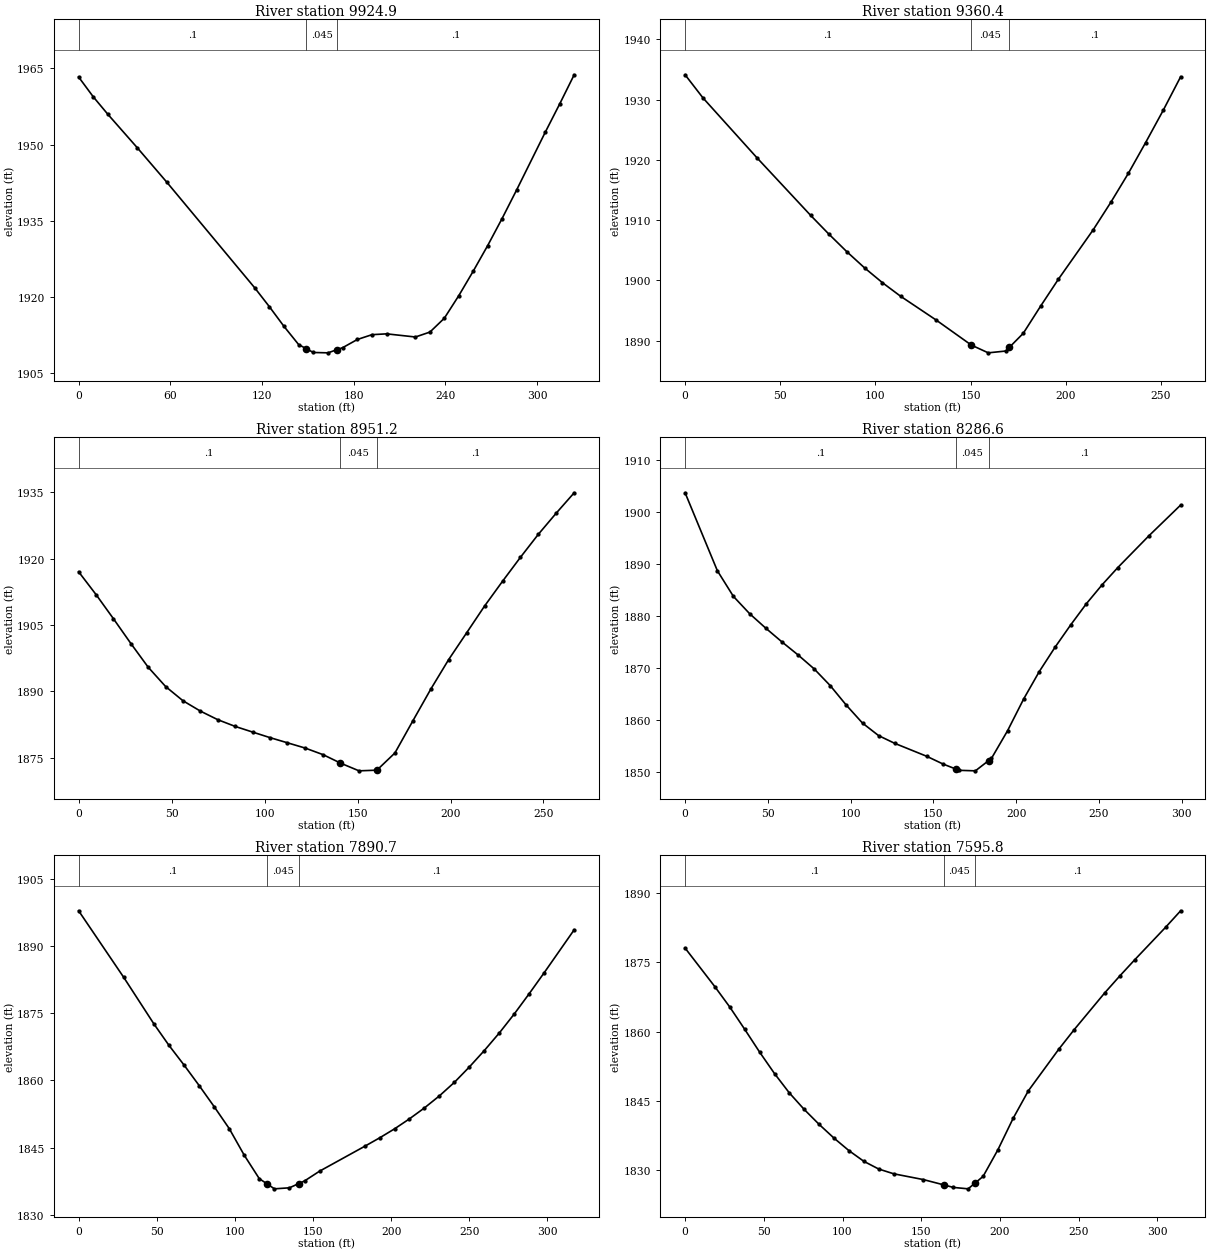
Type RM Length L Ch R = 1 ,9924.9  ,571.3,564.5,556.8
XS GIS Cut Line= 3
     1942350.507      289248.693      1942203.48      289386.551
     1942114.939      289471.621
#Sta/Elev= 28
       0 1963.32     9.6 1959.41    19.2 1955.95    38.4 1949.38    57.6 1942.64
   115.2 1921.81   124.8 1918.09   134.4  1914.2     144 1910.61   149.1 1909.79
   153.6 1909.06   163.2 1908.99   169.1 1909.62   172.8 1910.01   182.4 1911.62
     192 1912.57   201.6 1912.73   220.4 1912.11   229.9 1913.08   239.3  1915.8
   248.8 1920.26   258.2 1925.06   267.7 1930.12   277.1 1935.43   286.6 1941.05
   305.4 1952.46   314.9 1958.06   324.3 1963.76
#Mann= 3 , 0 , 0
       0      .1       0   149.1    .045       0   169.1      .1       0
Bank Sta=149.1,169.1
XS Rating Curve= 0 ,0
Exp/Cntr=0.3,0.1

Type RM Length L Ch R = 1 ,9360.4  ,405.5,409.2,412.4
XS GIS Cut Line= 3
     1941955.216      288898.704     1941880.564      288995.926
     1941809.383      289113.982
#Sta/Elev= 23
       0 1934.12     9.4 1930.28    37.7 1920.37      66 1910.78    75.4 1907.73
    84.9 1904.79    94.3 1902.08   103.7 1899.62   113.2 1897.38   131.8 1893.45
   150.4 1889.27   159.3 1887.98   168.5 1888.28   170.4 1888.89   177.7 1891.22
   186.9 1895.77   196.1 1900.17   214.5 1908.42   223.7 1912.95   232.9 1917.75
     242 1922.87   251.2  1928.2   260.4 1933.79
#Mann= 3 , 0 , 0
       0      .1       0   150.4    .045       0   170.4      .1       0
Bank Sta=150.4,170.4
XS Rating Curve= 0 ,0
Exp/Cntr=0.3,0.1

Type RM Length L Ch R = 1 ,8951.2  ,668.6,664.6,660.6
XS GIS Cut Line= 3
     1941595.841      288735.509     1941524.661      288822.315
     1941427.439      288942.107
#Sta/Elev= 30
       0    1917     9.4 1911.83    18.7  1906.4    28.1 1900.78    37.4 1895.43
    46.8 1891.05    56.1 1887.85    65.5  1885.5    74.8 1883.57    84.2 1882.04
    93.6 1880.76   102.9 1879.51   112.3 1878.34   121.9 1877.14   131.5 1875.65
   140.4 1873.84   141.2 1873.68   150.8    1872   160.4 1872.15   170.1 1876.04
   179.8 1883.34   189.4 1890.48     199 1897.15   208.7 1903.22   218.3 1909.25
     228 1914.87   237.6 1920.27   247.2 1925.46   256.9 1930.28   266.5 1934.86
#Mann= 3 , 0 , 0
       0      .1       0   140.4    .045       0   160.4      .1       0
Bank Sta=140.4,160.4
XS Rating Curve= 0 ,0
Exp/Cntr=0.3,0.1

Type RM Length L Ch R = 1 ,8286.6  ,397.3,396,394.6
XS GIS Cut Line= 3
     1941002.091      288426.482     1940899.661      288603.565
     1940885.772      288697.315
#Sta/Elev= 30
       0 1903.71    19.5 1888.73    29.2  1883.8      39 1880.48    48.7 1877.71
    58.4 1875.09    68.2 1872.57    77.9  1869.9    87.7 1866.66    97.4 1862.91
   107.2 1859.46   116.9 1857.06   126.6 1855.58   146.1 1853.07   155.9 1851.59
   163.4 1850.66   165.6 1850.39   175.4 1850.29   183.4 1852.26   185.1 1852.68
   194.8 1857.98   204.6 1864.12     214 1869.37   223.5 1874.03     233 1878.34
   242.5 1882.42     252 1886.05   261.4 1889.33   280.4  1895.5   299.4 1901.35
#Mann= 3 , 0 , 0
       0      .1       0   163.4    .045       0   183.4      .1       0
Bank Sta=163.4,183.4
XS Rating Curve= 0 ,0
Exp/Cntr=0.3,0.1

Type RM Length L Ch R = 1 ,7890.7  ,288.9,294.8,300.3
XS GIS Cut Line= 3
     1940634.036      288258.079     1940562.855      288405.648
     1940536.814       288556.69
#Sta/Elev= 30
       0 1897.82    28.9 1882.96    48.2 1872.59    57.8 1867.83    67.5 1863.42
    77.1 1858.88    86.7 1854.18    96.4 1849.26     106 1843.33   115.6 1838.12
   120.7 1836.93   125.3 1835.85   134.9 1836.08   140.7    1837   144.6 1837.62
   154.2 1839.79     183 1845.32   192.6 1847.21   202.2 1849.23   211.7 1851.45
   221.3 1853.89   230.9 1856.58   240.5  1859.6     250    1863   259.6 1866.67
   269.2 1870.59   278.8 1874.84   288.4 1879.38     298 1884.06   317.1 1893.58
#Mann= 3 , 0 , 0
       0      .1       0   120.7    .045       0   140.7      .1       0
Bank Sta=120.7,140.7
XS Rating Curve= 0 ,0
Exp/Cntr=0.3,0.1

Type RM Length L Ch R = 1 ,7595.8  ,390.8,387.3,383.7
XS GIS Cut Line= 3
     1940411.271      288186.193     1940286.271      288340.707
     1940236.466      288445.579
#Sta/Elev= 30
       0 1878.09    18.9 1869.74    28.4 1865.32    37.9 1860.49    47.3 1855.59
    56.8 1850.92    66.2 1846.74    75.7 1843.14    85.2  1839.9    94.6 1836.94
   104.1 1834.23   113.6 1831.91     123 1830.25   132.5 1829.22   151.4 1827.96
   164.2 1826.83   170.4 1826.27   179.8 1825.96   184.2 1827.21   189.3 1828.65
   198.7 1834.41   208.4 1841.23   218.1 1847.21   237.4  1856.2   247.1  1860.4
   266.5 1868.36   276.1 1872.04   285.8 1875.62   305.2 1882.58   314.8 1886.17
#Mann= 3 , 0 , 0
       0      .1       0   164.2    .045       0   184.2      .1       0
Bank Sta=164.2,184.2
XS Rating Curve= 0 ,0
Exp/Cntr=0.3,0.1

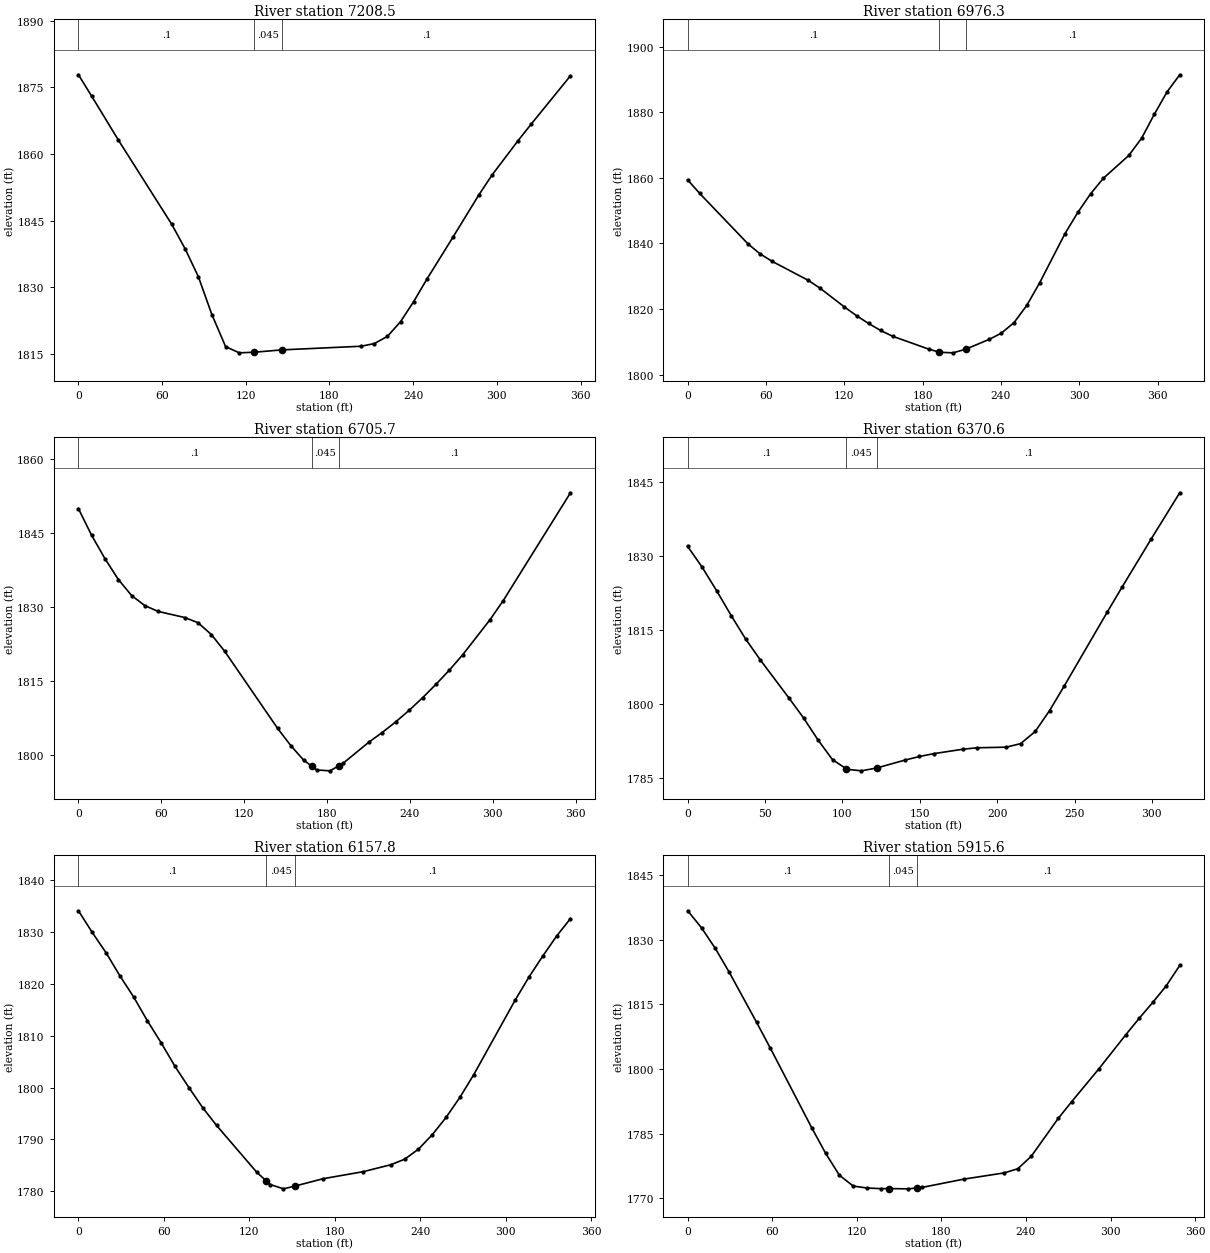
Type RM Length L Ch R = 1 ,7208.5  ,228.1,232.2,235.7
XS GIS Cut Line= 4
     1940088.354      288000.429     1940029.327      288062.929
     1939973.771      288154.943     1939909.535      288300.776
#Sta/Elev= 23
       0 1877.85     9.6 1872.97    28.7  1863.1    66.9 1844.16    76.4 1838.69
      86 1832.34    95.7  1823.8   105.5 1816.61   115.3  1815.2   126.1 1815.34
   146.1 1815.87   202.8 1816.69   212.2 1817.29   221.6 1818.92     231 1822.24
   240.3 1826.71   249.7 1831.73   268.4 1841.19   287.2 1850.83   296.6 1855.28
   315.3 1863.04   324.7 1866.76   352.8 1877.62
#Mann= 3 , 0 , 0
       0      .1       0   126.1    .045       0   146.1      .1       0
Bank Sta=126.1,146.1
XS Rating Curve= 0 ,0
Exp/Cntr=0.3,0.1

Type RM Length L Ch R = 1 ,6976.3  ,270.7,270.7,270.3
XS GIS Cut Line= 4
     1939932.647      287917.801       1939819.8      288013.287
     1939760.772      288084.468     1939713.897       288212.94
#Sta/Elev= 30
       0 1859.37     9.2 1855.26    46.2 1839.88    55.4 1836.85    64.7 1834.55
    92.4 1828.76   101.6 1826.31   120.1 1820.63   129.4 1817.97   138.6  1815.6
   147.8 1813.48   157.1 1811.69   184.8 1807.77   192.9 1806.83   203.3 1806.65
   212.9 1807.74     231 1810.75   240.3 1812.64   250.1 1815.89   259.8 1821.11
   269.6 1827.95   289.1 1843.01   298.9 1849.46   308.7 1855.15   318.4 1859.85
     338 1866.85   347.8 1872.11   357.5 1879.38   367.3 1886.23     377 1891.45
#Mann= 3 , 0 , 0
       0      .1       0   192.9    .045       0   212.9      .1       0
Bank Sta=192.9,212.9
XS Rating Curve= 0 ,0
Exp/Cntr=0.3,0.1

Type RM Length L Ch R = 1 ,6705.7  ,340.8,335.1,329.7
XS GIS Cut Line= 4
      1939672.23      287766.759     1939588.897      287872.662
     1939535.077      287938.634     1939458.689      288051.482
#Sta/Elev= 30
       0 1850.01     9.6 1844.58    19.2 1839.87    28.9 1835.65    38.5  1832.4
    48.1 1830.35    57.8 1829.17      77 1827.94    86.6 1826.88    96.3 1824.47
   105.9 1821.08   144.2 1805.45   153.7 1801.98   163.1    1799   168.8 1797.82
   172.6 1797.03   182.1 1796.85   188.8 1797.93   191.5 1798.36   210.4  1802.7
   219.9 1804.62   229.6 1806.76   239.4 1809.12   249.1 1811.66   258.8 1814.39
   268.6 1817.29   278.3 1820.43   297.8 1827.44   307.5 1831.36   356.2 1853.24
#Mann= 3 , 0 , 0
       0      .1       0   168.8    .045       0   188.8      .1       0
Bank Sta=168.8,188.8
XS Rating Curve= 0 ,0
Exp/Cntr=0.3,0.1

Type RM Length L Ch R = 1 ,6370.6  ,212.7,212.7,212.6
XS GIS Cut Line= 3
     1939312.855      287660.857     1939238.202      287811.898
     1939213.897      287959.468
#Sta/Elev= 28
       0 1832.01     9.4 1827.78    18.7 1823.03    28.1    1818    37.4 1813.26
    46.8 1809.06    65.5 1801.25    74.9 1797.23    84.2 1792.78    93.6 1788.77
   102.3 1786.97     103 1786.82   112.3 1786.51   122.3  1787.1   140.4 1788.69
   149.8 1789.42   159.1    1790   177.8 1790.89   187.2 1791.19   205.9 1791.31
   215.2 1792.03   224.6 1794.49   233.9 1798.74   243.3 1803.68   271.3 1818.78
   280.6  1823.7   299.4 1833.45     318  1842.9
#Mann= 3 , 0 , 0
       0      .1       0   102.3    .045       0   122.3      .1       0
Bank Sta=102.3,122.3
XS Rating Curve= 0 ,0
Exp/Cntr=0.3,0.1

Type RM Length L Ch R = 1 ,6157.8  ,235.8,242.3,248.6
XS GIS Cut Line= 4
     1939126.549      287590.707     1939072.729      287682.721
     1939031.063      287766.054      1938987.66      287904.943
#Sta/Elev= 30
       0 1834.12     9.7 1829.93    19.4 1826.02    29.1 1821.56    38.8 1817.46
    48.4 1812.88    58.1 1808.62    67.8 1804.08    77.5 1800.02    87.2 1796.13
    96.9 1792.71   125.2 1783.65   131.9 1781.98   134.6  1781.3   143.9 1780.47
   151.9    1781   171.8 1782.43   199.8 1783.78   219.2 1785.12   228.9 1786.18
   238.6 1788.12   248.3 1790.91     258 1794.25   267.7 1798.12   277.4 1802.49
   306.5 1816.89   316.2 1821.35   325.9  1825.4   335.6 1829.25   345.3 1832.61
#Mann= 3 , 0 , 0
       0      .1       0   131.9    .045       0   151.9      .1       0
Bank Sta=131.9,151.9
XS Rating Curve= 0 ,0
Exp/Cntr=0.3,0.1

Type RM Length L Ch R = 1 ,5915.6  ,312.1,316.4,320.8
XS GIS Cut Line= 3
     1938948.272      287478.565     1938812.855      287633.079
     1938752.091      287763.287
#Sta/Elev= 28
       0  1836.7     9.8 1832.75    19.6 1827.95    29.4 1822.48    48.9  1810.8
    58.7 1804.78      88 1786.35    97.8 1780.46   107.6 1775.35   117.4 1772.83
   127.2 1772.37     137 1772.23   142.5 1772.24   156.5 1772.18   162.5 1772.38
   166.3 1772.51   195.7 1774.42   224.6 1775.88   234.2 1776.84   243.8 1779.75
   262.9 1788.52   272.5 1792.43   291.7 1800.01   310.8 1807.92   320.4 1811.77
     330 1815.44   339.6 1819.31   349.1 1824.01
#Mann= 3 , 0 , 0
       0      .1       0   142.5    .045       0   162.5      .1       0
Bank Sta=142.5,162.5
XS Rating Curve= 0 ,0
Exp/Cntr=0.3,0.1

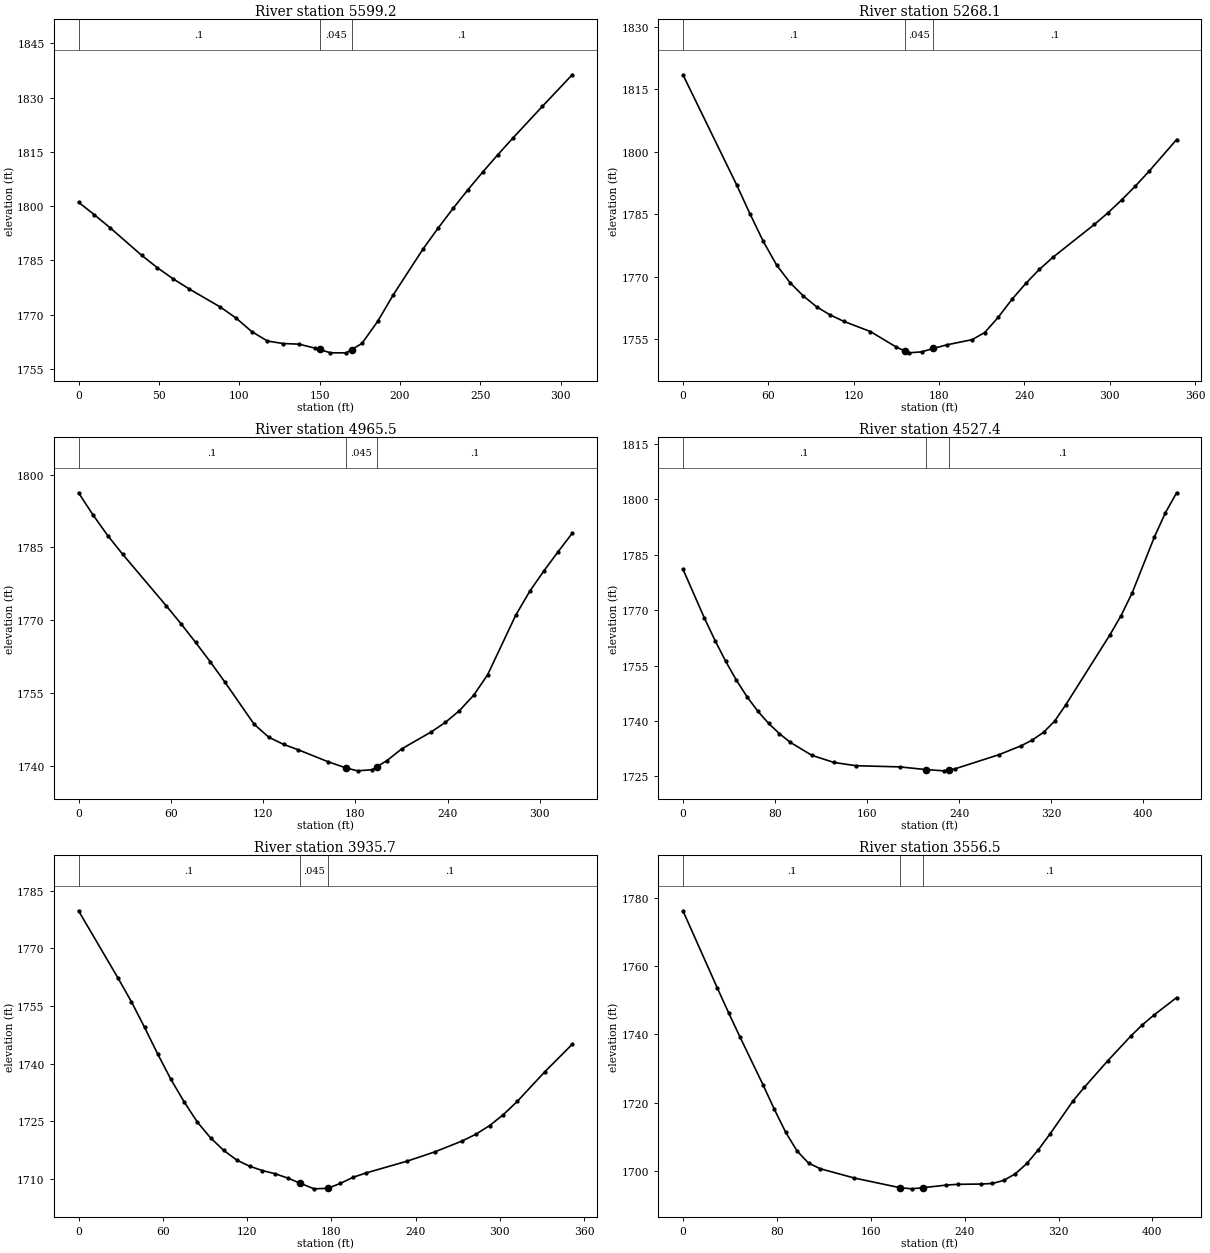
Type RM Length L Ch R = 1 ,5599.2  ,341,331.1,320.5
XS GIS Cut Line= 3
     1938718.454      287340.544     1938566.544      287464.242
       1938497.1      287551.048
#Sta/Elev= 30
       0 1801.11     9.8 1797.65    19.6 1794.06    39.2 1786.46      49 1783.01
    58.8 1779.95    68.6  1777.2    88.2 1772.13      98 1769.08   107.8 1765.33
   117.5 1762.74   127.3 1762.04   137.1 1761.87   146.9  1760.8   149.9  1760.4
   156.7 1759.48   166.5 1759.47   169.9 1760.37   176.3 1762.07   186.1 1768.18
   195.9 1775.58   214.4 1788.24   223.7 1793.96     233  1799.4   242.2 1804.54
   251.5 1809.48   260.8 1814.22     270 1818.75   288.5 1827.59   307.1 1836.34
#Mann= 3 , 0 , 0
       0      .1       0   149.9    .045       0   169.9      .1       0
Bank Sta=149.9,169.9
XS Rating Curve= 0 ,0
Exp/Cntr=0.3,0.1

Type RM Length L Ch R = 1 ,5268.1  ,306.3,302.6,299
XS GIS Cut Line= 4
     1938507.951      287067.107     1938410.294      287169.103
     1938377.742      287232.037     1938319.149      287353.565
#Sta/Elev= 30
       0 1818.49    37.7 1792.09    47.1 1785.12    56.5 1778.47    65.9 1772.77
    75.3 1768.56    84.7 1765.35    94.1 1762.74   103.6  1760.8     113 1759.29
   131.8 1756.83   150.1 1753.08     156 1752.17   158.9 1751.72   167.8 1751.96
     176 1752.78   185.5 1753.64   203.2 1754.88   212.1 1756.59   221.7 1760.29
   231.3 1764.58     241 1768.39   250.6 1771.78   260.2  1774.7   289.2 1782.55
   298.8 1785.36   308.4 1788.45   318.1 1791.79   327.7 1795.34     347 1802.93
#Mann= 3 , 0 , 0
       0      .1       0     156    .045       0     176      .1       0
Bank Sta=156,176
XS Rating Curve= 0 ,0
Exp/Cntr=0.3,0.1

Type RM Length L Ch R = 1 ,4965.5  ,423.3,438.1,453
XS GIS Cut Line= 4
     1938204.131      286966.195     1938128.176      287063.851
     1938093.454      287163.678     1938045.711      287241.803
#Sta/Elev= 30
       0 1796.25     9.5 1791.65      19 1787.44    28.6 1783.63    57.1 1772.97
    66.6 1769.31    76.1 1765.47    85.6 1761.49    95.2 1757.28   114.2 1748.61
   123.7 1745.95   133.3 1744.48   142.9 1743.36   162.2 1740.91   173.9 1739.63
   181.4 1739.03     191 1739.27   193.9 1739.84   200.6 1741.15   210.2 1743.56
   229.4 1747.05   238.6 1749.02   247.7 1751.43   256.9 1754.57     266  1758.8
   284.3 1771.06   293.5 1776.04   302.7 1780.22   311.8 1784.11     321 1787.91
#Mann= 3 , 0 , 0
       0      .1       0   173.9    .045       0   193.9      .1       0
Bank Sta=173.9,193.9
XS Rating Curve= 0 ,0
Exp/Cntr=0.3,0.1

Type RM Length L Ch R = 1 ,4527.4  ,595.9,591.7,588.9
XS GIS Cut Line= 4
     1937978.437      286720.969     1937882.951      286757.862
     1937752.742      286855.518     1937659.426      286990.067
#Sta/Elev= 30
       0 1781.12    18.6 1767.91    27.9 1761.79    37.2 1756.14    46.5 1751.02
    55.8 1746.51    65.1 1742.64    74.4 1739.36    83.8 1736.58    93.1 1734.26
   111.9 1730.72   131.1 1728.78   150.2 1727.89   188.5 1727.57   210.8 1726.85
   226.8  1726.5   230.8 1726.73   236.4 1727.05   274.8  1730.9     294 1733.31
   303.6 1734.86   313.3 1736.93   322.9 1739.95   332.6 1744.37   371.1 1763.39
   380.7 1768.56   390.3  1774.7   409.6 1789.82   419.2 1796.41   428.9  1801.8
#Mann= 3 , 0 , 0
       0      .1       0   210.8    .045       0   230.8      .1       0
Bank Sta=210.8,230.8
XS Rating Curve= 0 ,0
Exp/Cntr=0.3,0.1

Type RM Length L Ch R = 1 ,3935.7  ,375.9,379.2,380.8
XS GIS Cut Line= 4
     1937485.381      286315.154     1937405.086      286380.258
     1937335.642      286454.042     1937287.899      286592.931
#Sta/Elev= 30
       0 1779.79    28.2 1762.24    37.6 1756.18      47  1749.5    56.4 1742.54
    65.8 1735.94    75.2 1730.13    84.6 1724.85      94 1720.75   103.4 1717.49
   112.6 1714.99   121.8 1713.38     131 1712.24   140.2  1711.4   149.4 1710.24
   157.6 1708.98   167.8 1707.49   177.6 1707.63   186.3 1708.88   195.5 1710.48
   204.7 1711.61   234.1  1714.7   253.6 1717.08   273.2 1719.93     283 1721.69
   292.8 1723.94   302.6  1726.8   312.4  1730.2     332 1737.89   351.6 1745.07
#Mann= 3 , 0 , 0
       0      .1       0   157.6    .045       0   177.6      .1       0
Bank Sta=157.6,177.6
XS Rating Curve= 0 ,0
Exp/Cntr=0.3,0.1

Type RM Length L Ch R = 1 ,3556.5  ,350.3,361.5,372.5
XS GIS Cut Line= 3
     1937231.909      286117.671     1937114.722      286187.115
     1936891.197      286362.897
#Sta/Elev= 30
       0 1776.14    29.2 1753.66    38.9 1746.36    48.6 1739.27    68.1 1725.39
    77.8 1718.21    87.6  1711.4    97.3 1705.94     107 1702.45   116.8  1700.8
     146 1698.07   184.7 1695.26     195 1694.91   204.7 1695.25   224.5 1696.01
   234.3 1696.23   253.9 1696.31   263.7 1696.48   273.5  1697.4   283.3 1699.33
   293.1 1702.34   302.9 1706.37   312.7 1710.92   332.3 1720.57   342.1 1724.62
   361.8 1732.27   381.4 1739.47   391.2 1742.75     401 1745.59   420.6 1750.78
#Mann= 3 , 0 , 0
       0      .1       0   184.7    .045       0   204.7      .1       0
Bank Sta=184.7,204.7
XS Rating Curve= 0 ,0
Exp/Cntr=0.3,0.1

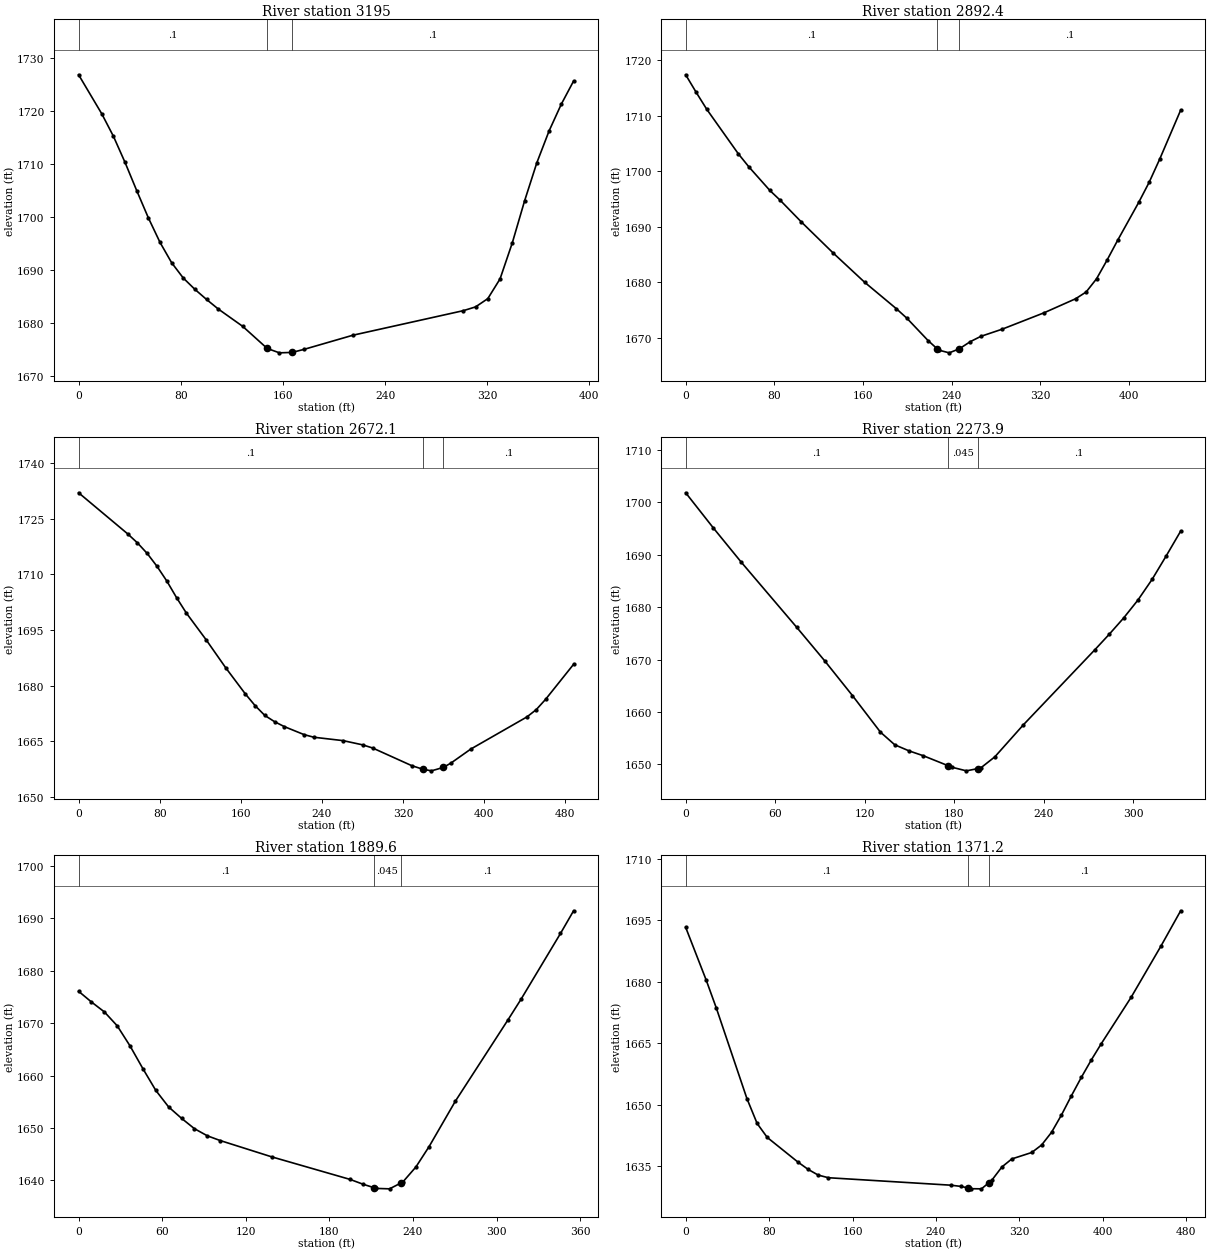
Type RM Length L Ch R = 1 ,3195    ,304.9,302.6,300.2
XS GIS Cut Line= 4
     1937038.767      285896.317      1936930.26      285909.338
     1936808.732      285937.549     1936685.034      286028.695
#Sta/Elev= 29
       0 1726.84    18.2 1719.46    27.3 1715.23    36.4  1710.3    45.5 1705.01
    54.6 1699.88    63.8 1695.22    72.9 1691.39      82 1688.51    91.1 1686.38
   100.2 1684.48   109.3 1682.69   128.5 1679.41   147.2 1675.35   147.7 1675.24
   157.3 1674.41   167.2 1674.49   176.5 1675.06   214.8 1677.73   301.3 1682.36
   310.9 1683.07   320.5 1684.63   330.1 1688.35   339.7 1695.15   349.3 1703.05
   358.9 1710.24   368.5 1716.25   378.1 1721.31   387.7 1725.66
#Mann= 3 , 0 , 0
       0      .1       0   147.2    .045       0   167.2      .1       0
Bank Sta=147.2,167.2
XS Rating Curve= 0 ,0
Exp/Cntr=0.3,0.1

Type RM Length L Ch R = 1 ,2892.4  ,233.2,220.3,207.5
XS GIS Cut Line= 4
     1936973.662      285690.154     1936813.072       285631.56
     1936704.565      285668.452     1936561.336      285742.237
#Sta/Elev= 30
       0  1717.4     9.5 1714.23      19 1711.19    47.5 1703.17      57 1700.82
      76 1696.56    85.5 1694.76   104.5 1690.87     133 1685.32   161.4 1680.05
     190 1675.29   199.6 1673.56   218.7 1669.54   226.9 1668.06   228.2 1667.82
   237.8 1667.32   246.9 1668.04   256.9 1669.34   266.4 1670.29   285.6 1671.58
   323.5 1674.54   351.9 1677.06   361.4 1678.28   370.8 1680.66   380.3 1684.03
   389.8 1687.58   408.8  1694.4   418.2 1698.01   427.7 1702.17   446.7 1711.03
#Mann= 3 , 0 , 0
       0      .1       0   226.9    .045       0   246.9      .1       0
Bank Sta=226.9,246.9
XS Rating Curve= 0 ,0
Exp/Cntr=0.3,0.1

Type RM Length L Ch R = 1 ,2672.1  ,412.7,398.2,383.5
XS GIS Cut Line= 4
     1936897.708      285410.206      1936615.59       285477.48
     1936550.485      285549.094     1936483.211      285625.049
#Sta/Elev= 30
       0 1732.03    48.3 1720.97      58 1718.52    67.7 1715.65    77.3  1712.2
      87 1708.22    96.7  1703.7   106.3 1699.57   125.7  1692.4     145 1684.85
   164.4 1677.78     174 1674.62   183.7 1671.94   193.4 1670.24     203 1668.92
   222.4 1666.77     232 1666.06     261 1665.14   280.4 1663.99     290 1663.16
   328.7 1658.38   339.9  1657.4   348.1 1656.99   359.9 1657.92   367.5 1659.12
   386.8 1662.85   442.2 1671.53   451.4 1673.49   460.6 1676.26   488.3 1685.74
#Mann= 3 , 0 , 0
       0      .1       0   339.9    .045       0   359.9      .1       0
Bank Sta=339.9,359.9
XS Rating Curve= 0 ,0
Exp/Cntr=0.3,0.1

Type RM Length L Ch R = 1 ,2273.9  ,378.8,384.3,389.8
XS GIS Cut Line= 3
     1936240.156      285219.233     1936209.774      285336.421
     1936177.222      285544.754
#Sta/Elev= 24
       0 1701.77    18.6 1695.05    37.2 1688.57    74.5 1676.12    93.1 1669.79
   111.8 1663.14   130.6 1656.16   140.2 1653.75   149.8 1652.59   159.4 1651.66
   175.8 1649.79   178.6 1649.47   188.2 1648.79   195.8 1649.21   197.7 1649.31
   207.3 1651.46   226.5 1657.58   274.4 1671.87     284 1674.81   293.6 1677.89
   303.2 1681.31   312.8 1685.29   322.3 1689.79   331.9 1694.46
#Mann= 3 , 0 , 0
       0      .1       0   175.8    .045       0   195.8      .1       0
Bank Sta=175.8,195.8
XS Rating Curve= 0 ,0
Exp/Cntr=0.3,0.1

Type RM Length L Ch R = 1 ,1889.6  ,525.1,518.4,511.1
XS GIS Cut Line= 3
     1935918.975       285160.64      1935845.19      285288.678
     1935769.235       285481.82
#Sta/Elev= 27
       0 1676.09     9.2 1674.05    18.5 1672.15    27.7  1669.5    36.9 1665.66
    46.2 1661.28    55.4 1657.16    64.6    1654    73.9 1651.82    83.1 1649.85
    92.4 1648.48   101.6 1647.58   138.5 1644.47     195 1640.14   204.4 1639.21
   211.7  1638.6   213.8 1638.43   223.2 1638.35   231.7 1639.51   232.7 1639.65
   242.1 1642.52   251.6 1646.43   270.4 1655.08   308.2 1670.63   317.6 1674.58
   345.9 1687.14   355.3 1691.47
#Mann= 3 , 0 , 0
       0      .1       0   211.7    .045       0   231.7      .1       0
Bank Sta=211.7,231.7
XS Rating Curve= 0 ,0
Exp/Cntr=0.3,0.1

Type RM Length L Ch R = 1 ,1371.2  ,382.1,368.4,354.3
XS GIS Cut Line= 3
     1935346.058      284991.369     1935315.676      285293.018
     1935317.847      285464.459
#Sta/Elev= 30
       0 1693.32    19.6  1680.5    29.3 1673.69    58.7 1651.55    68.5 1645.46
    78.2 1642.05   107.6 1636.04   117.4 1634.25   127.1 1632.85   136.9 1632.21
   254.3 1630.39   264.1 1630.09   270.7 1629.71   273.8 1629.53   283.6  1629.5
   290.7 1630.99   293.4 1631.56   303.2 1634.84   312.7  1636.8   331.8 1638.37
   341.3 1640.21   350.8  1643.3   360.3 1647.52   369.8  1652.2   379.4 1656.73
   388.9 1660.95   398.4  1664.9     427 1676.21   455.6 1688.71   474.6 1697.37
#Mann= 3 , 0 , 0
       0      .1       0   270.7    .045       0   290.7      .1       0
Bank Sta=270.7,290.7
XS Rating Curve= 0 ,0
Exp/Cntr=0.3,0.1

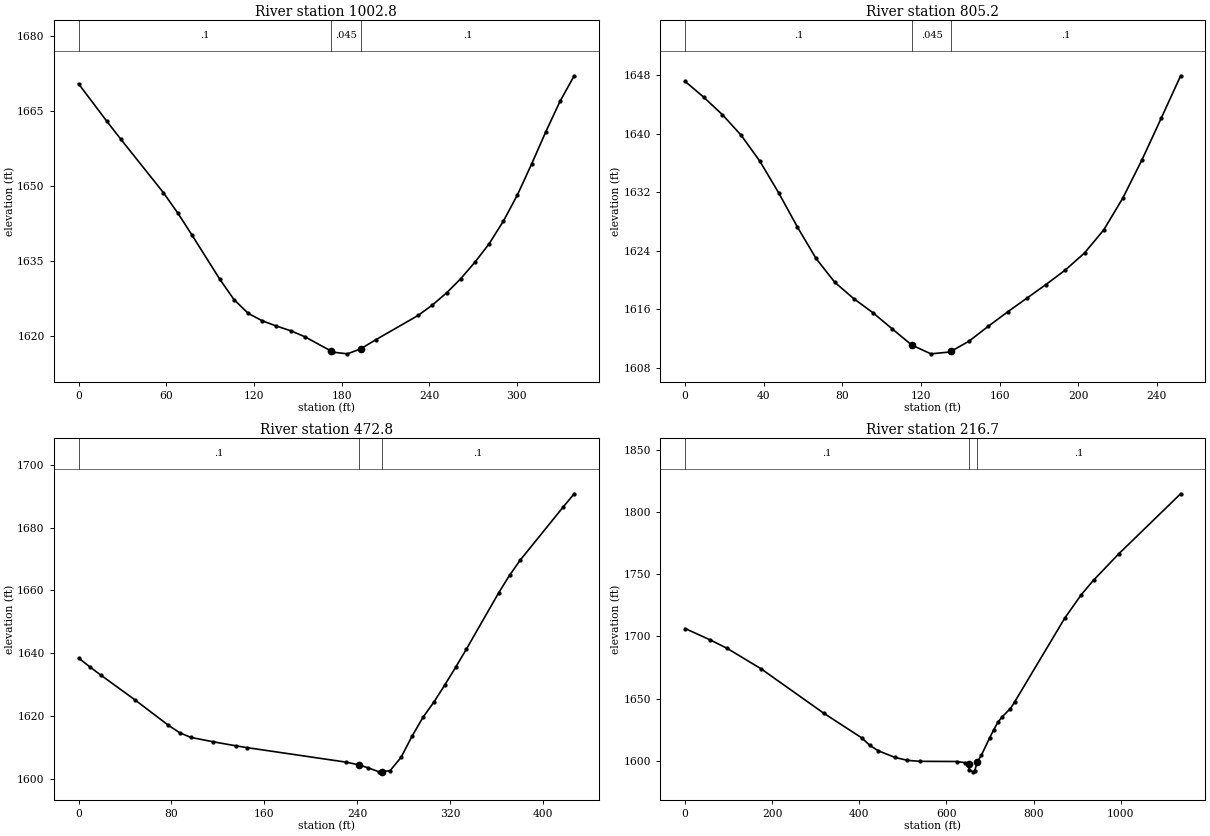
Type RM Length L Ch R = 1 ,1002.8  ,186.6,197.7,208.6
XS GIS Cut Line= 3
     1934885.989      285149.789     1934931.562      285266.976
     1935027.048      285457.949
#Sta/Elev= 30
       0 1670.41    19.3 1662.93      29 1659.29      58 1648.65    67.7 1644.63
    77.4 1640.23    96.7 1631.27   106.4  1627.2   116.1 1624.46   125.7 1622.98
   135.4 1621.92   145.2 1620.98   154.8 1619.79     173 1616.89   174.3 1616.69
     184 1616.36     193 1617.35   203.4 1619.18   232.5 1624.07   242.2 1626.15
   251.9 1628.57   261.6 1631.42   271.3 1634.72     281 1638.41   290.7 1642.91
   300.4 1648.22   310.1 1654.39   319.8 1660.84   329.6 1666.97   339.2 1672.04
#Mann= 3 , 0 , 0
       0      .1       0     173    .045       0     193      .1       0
Bank Sta=173,193
XS Rating Curve= 0 ,0
Exp/Cntr=0.3,0.1

Type RM Length L Ch R = 1 ,805.2   ,330.2,332.4,334.4
XS GIS Cut Line= 3
     1934790.503      285234.424     1934786.162      285310.379
     1934794.843       285486.16
#Sta/Elev= 29
       0 1647.12     9.5 1644.95      19 1642.57    28.5 1639.77      38 1636.24
    47.6 1631.91    57.1 1627.26    66.6 1622.96    76.1 1619.71    85.9 1617.45
    95.6 1615.54   105.4 1613.34   115.2 1611.16   115.5 1611.12     125 1609.94
   134.7 1610.19   135.5 1610.31   144.5 1611.68   154.3 1613.71   164.1 1615.67
   173.8 1617.52   183.6  1619.4   193.4 1621.37   203.2  1623.7     213 1626.86
   222.7  1631.2   232.5 1636.45   242.3 1642.14   252.1 1647.88
#Mann= 3 , 0 , 0
       0      .1       0   115.5    .045       0   135.5      .1       0
Bank Sta=115.5,135.5
XS Rating Curve= 0 ,0
Exp/Cntr=0.3,0.1

Type RM Length L Ch R = 1 ,472.8   ,257.2,256,254.7
XS GIS Cut Line= 4
     1934545.277      285245.275     1934492.868       285400.82
      1934487.66      285542.747     1934521.514      285658.632
#Sta/Elev= 28
       0 1638.41     9.7  1635.6    19.3 1632.94    48.3 1625.16    77.2 1617.04
    86.9 1614.65    96.6 1613.15   115.9 1611.74   135.2 1610.48   144.8  1609.9
   230.4 1605.26   241.2 1604.41   249.4 1603.45   258.8 1602.17   261.2 1602.26
   268.3 1602.53   277.8 1606.79   287.2 1613.51   296.7 1619.56   306.2 1624.48
   315.4 1629.82   324.7 1635.43     334 1641.24   361.9 1659.22   371.2 1664.76
   380.4 1669.61   417.6 1686.61   426.9 1690.75
#Mann= 3 , 0 , 0
       0      .1       0   241.2    .045       0   261.2      .1       0
Bank Sta=241.2,261.2
XS Rating Curve= 0 ,0
Exp/Cntr=0.3,0.1

Type RM Length L Ch R = 1 ,216.7   ,212.6,216.7,220.8
BEGIN DESCRIPTION:
Know WSEL & Channel Invert from Lettered XS 'C'
END DESCRIPTION:
XS GIS Cut Line= 6
     1934590.257      285038.519     1934244.102      285249.562
     1934245.555      285477.676     1934245.607      285543.047
     1934245.745      285715.561     1934416.142      285919.981
#Sta/Elev= 30
       0 1706.34    57.9 1697.13    96.5 1690.37   173.8 1674.06   318.5 1638.13
   405.4 1618.35   424.4  1612.2   443.4 1607.95   481.5 1602.64     510 1600.27
   538.5 1599.46     624 1599.32   642.9 1598.35   650.6 1597.46   652.2 1592.27
   661.6    1591     665    1592   670.6  1598.9   680.2 1604.41   698.9 1618.23
   708.5 1624.91   718.1 1630.91   727.7 1635.22   746.8 1641.92   756.4  1647.2
   871.4 1714.64   909.4 1733.56     938 1745.38     995 1766.28  1137.5 1814.76
#Mann= 3 , 0 , 0
       0      .1       0   650.6    .045       0   670.6      .1       0
Bank Sta=650.6,670.6
XS Rating Curve= 0 ,0
Exp/Cntr=0.3,0.1

Chan Stop Cuts=-1
Use User Specified Reach Order=0
Composite Channel Slope=5